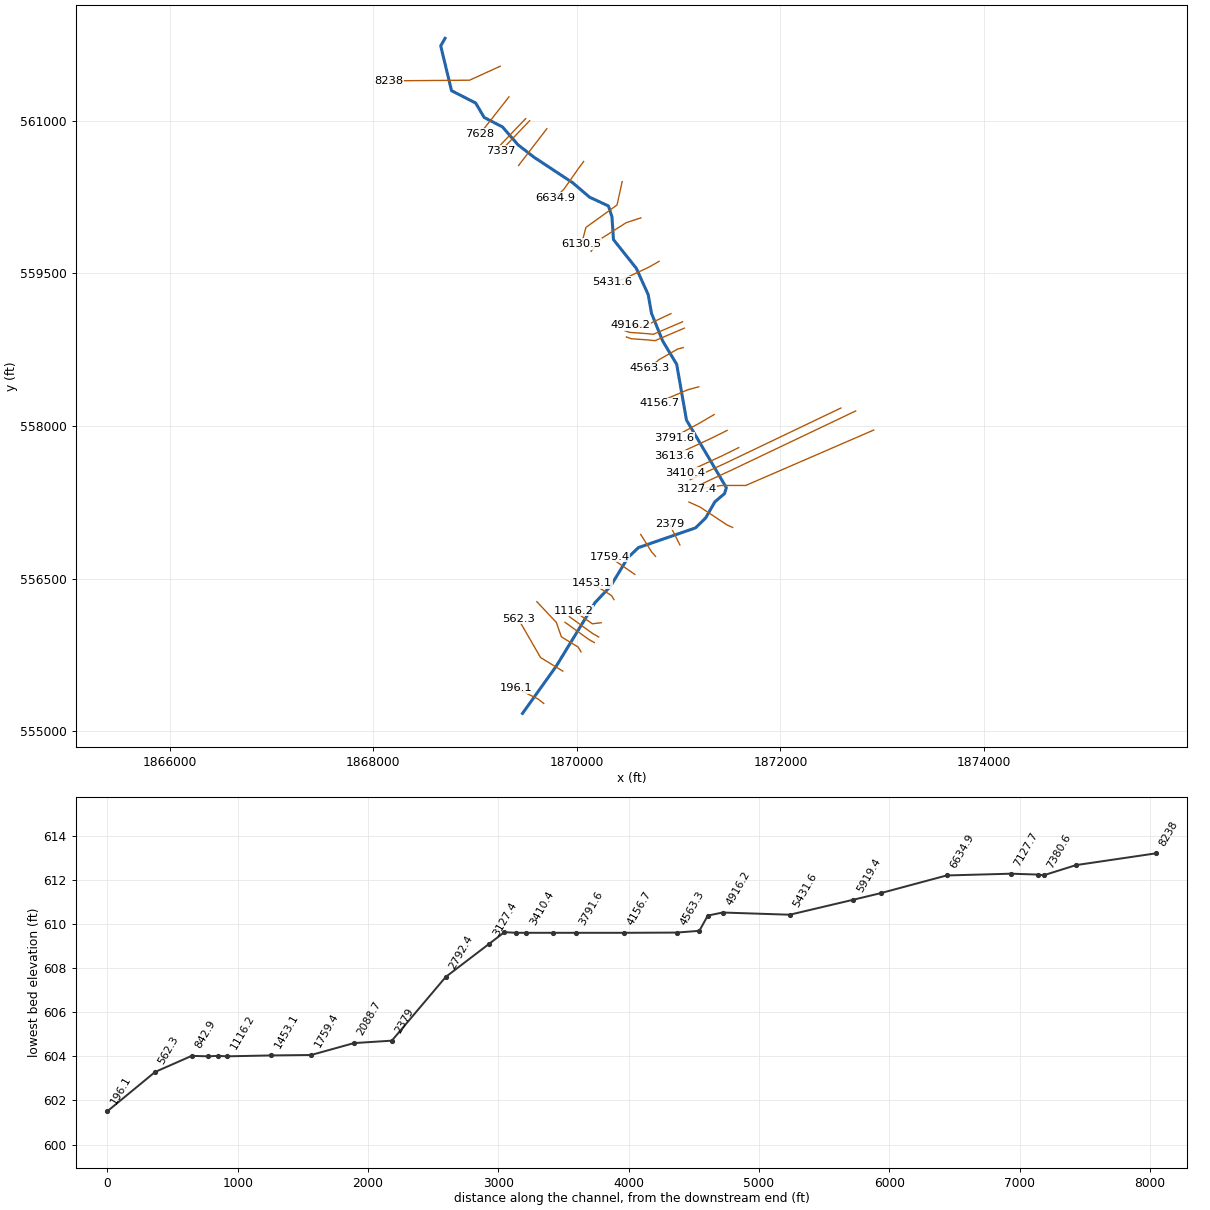
--- LEFTHANDCR.prj (project) ---

Proj Title=LEFTHANDCR
Current Plan=p01
Default Exp/Contr=0,0
English Units
Geom File=g01
Flow File=f01
Plan File=p01
BEGIN DESCRIPTION:
END DESCRIPTION:
DSS Export Rating Curves= 0
DSS Export Rating Curve Sorted= 0
DSS Export Volume Flow Curves= 0
DXF OffsetX= 0
DXF OffsetY= 0
DXF ScaleX= 0
DXF ScaleY= 0

--- LEFTHANDCR.p01 (plan) ---

Plan Title=Floodplain
Program Version=4.00
Geom File=g01
Flow File=f01
K Sum by GR=0
Std Step Tol=0.01
Critical Tol=0.01
Num of Std Step Trials=20
Max Error Tol=0.3
Flow Tol Ratio=0.001
Split Flow NTrial=30
Split Flow Tol=0.02
Split Flow Ratio=0.02
Log Output Level=0
Friction Slope Method=1
Unsteady Friction Slope Method=2
Unsteady Bridges Friction Slope Method=1
Global Log Level=0
CheckData=False
Run HTab=0
Run UNet=0
Run PostProcess=0
UNET Theta=0
UNET Theta Warmup=0
UNET ZTol=0
UNET ZSATol=0
UNET MxIter=0
UNET MaxInSteps=0
UNET DtIC=0
UNET DtMin=0
UNET MaxCRTS=0
UNET WFStab=0
UNET SFStab=0
UNET WFX=0
UNET SFX=0
UNET DSS MLevel=0
UNET DZMax Abort=0
UNET Convert EG Bridges=0
UNET Use Existing IB Tables=0
UNET Froude Limit=0
UNET Froude Power=0
Write IC File=0
Echo Input=False
Echo Output=False
Write Detailed=0

--- LEFTHANDCR.f01 (steady flow) ---

Flow Title=NFF Regression Equation
Program Version=4.10
Number of Profiles= 1
Profile Names=P100yr
River Rch & RM=LEFTHANDCR,Main            ,8238
5209.203
River Rch & RM=LEFTHANDCR,Main            ,2792.4
5413.365
Boundary for River Rch & Prof#=LEFTHANDCR,Main            , 1
Up Type= 0
Dn Type= 3
Dn Slope=0.005
DSS Import GetInterval= 0
DSS Import GetPeak= 0
DSS Import FillOption= 0

--- LEFTHANDCR.g01 (geometry) ---

Geom Title=USGS 10m DEM
Program Version=4.10

River Reach=LEFTHANDCR      ,Main
Reach XY= 30
      1868705.09      561809.273     1868662.381      561735.396
     1868768.892       561294.95     1869006.145      561173.351
     1869089.204      561031.929     1869269.166      560938.976
      1869421.51      560763.194     1869582.694        560638.7
     1869957.694      560391.304     1870125.663      560248.075
     1870310.559      560162.137      1870345.13      560055.387
     1870360.038      559831.408      1870584.27      559549.653
     1870701.458      559290.538     1870733.736       559107.45
     1870843.111      558836.616     1870981.131      558606.148
     1871077.486      558057.971     1871469.413      557393.908
     1871451.184      557335.314     1871356.131      557254.585
     1871266.288      557097.033     1871167.329      556999.377
     1870605.104      556804.861     1870501.965      556706.408
     1870331.666      556425.955     1870178.041      556263.225
      1869796.51      555638.195     1869466.422      555176.122

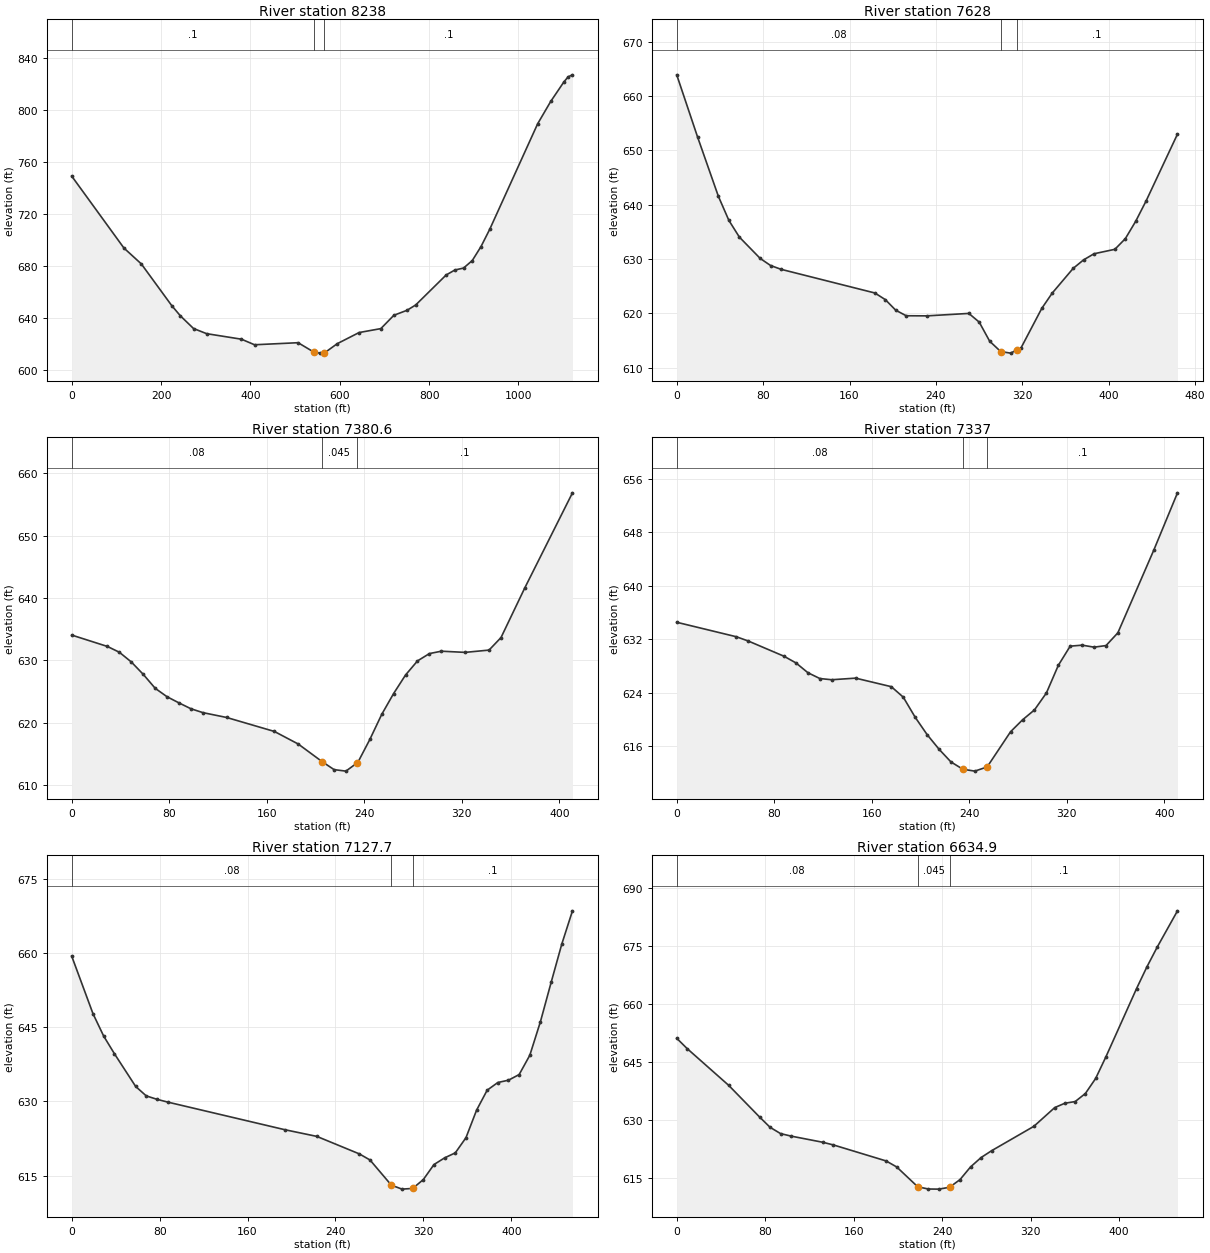
Type RM Length L Ch R = 1 ,8238    ,589.5,610,630.3
XS GIS Cut Line= 3
     1869247.178      561535.311     1868945.916      561397.745
     1868156.273      561391.988
#Sta/Elev= 30
       0  749.45   116.9  694.08   155.8  681.87     224  649.72   243.5   641.8
   272.7  632.14     302  628.18   379.9  623.92   409.2  619.64   506.7  621.22
   542.7  613.84   555.4   613.2   565.2  613.24   594.4  620.48   643.2  629.04
   691.9  632.07   721.1  642.34   750.4  646.15   769.9  650.26   838.1  673.35
   857.6  677.17   877.1  678.69   896.6  684.48   916.1  695.22   935.6   708.5
  1042.9  789.73  1072.1  806.91  1101.4  821.83  1111.1  825.86  1120.8   827.4
#Mann= 3 , 0 , 0
       0      .1       0   542.7    .045       0   565.2      .1       0
Bank Sta=542.7,565.2
XS Rating Curve= 0 ,0
Exp/Cntr=0.3,0.1

Type RM Length L Ch R = 1 ,7628    ,248.8,247.4,244.8
XS GIS Cut Line= 2
     1869333.374      561234.209     1869046.916      560869.626
#Sta/Elev= 30
       0   663.9    19.3  652.46    38.6  641.52    48.3   637.1      58  634.03
    77.3   630.1    86.9   628.8    96.6   628.1   183.5  623.74   193.2  622.51
   202.8  620.57   212.5  619.55   231.8  619.53   270.5  619.98   280.1  618.38
   289.8  614.86     300  612.96   309.1  612.67     315  613.25   318.8  613.63
   338.1  620.93   347.7  623.72   367.1  628.27   376.7  629.83   386.4  630.96
   405.7  631.78   415.4  633.74     425  636.94   434.7  640.71   463.7  652.99
#Mann= 3 , 0 , 0
       0     .08       0     300    .045       0     315      .1       0
Bank Sta=300,315
XS Rating Curve= 0 ,0
Exp/Cntr=0.3,0.1

Type RM Length L Ch R = 1 ,7380.6  ,43.8,43.7,43.5
XS GIS Cut Line= 2
     1869497.436      561020.667     1869213.582      560723.792
#Sta/Elev= 30
       0  634.05    29.3  632.22    39.1  631.29    48.9  629.73    58.7  627.74
    68.5   625.5    78.2  624.15      88  623.16    97.8  622.22   107.6   621.6
   127.1  620.82   166.2  618.58   185.8  616.56   205.4  613.73   215.2  612.45
   224.9  612.21   233.6  613.46   234.7  613.62   244.5  617.29   254.3  621.33
     264  624.66   273.8  627.64   283.6   629.9   293.4  631.08   303.2  631.46
   322.7  631.27   342.3  631.64   352.1  633.65   371.6  641.62   410.7  656.88
#Mann= 3 , 0 , 0
       0     .08       0   205.4    .045       0   233.6      .1       0
Bank Sta=205.4,233.6
XS Rating Curve= 0 ,0
Exp/Cntr=0.3,0.1

Type RM Length L Ch R = 1 ,7337    ,206.8,209.3,211.6
XS GIS Cut Line= 2
     1869536.499      560999.834     1869252.645      560702.959
#Sta/Elev= 30
       0  634.54    48.9  632.37    58.7  631.73      88  629.45    97.8  628.45
   107.6  626.98   117.4  626.11   127.1  625.93   146.7  626.17     176  624.89
   185.8  623.32   195.6   620.3   205.4   617.7   215.2  615.51   224.9  613.62
   234.7  612.52   244.5  612.24   254.6  612.87   273.8  618.14   283.6  619.92
   293.4  621.41   303.2  623.95     313   628.1   322.7  630.96   332.5  631.11
   342.3  630.81   352.1  631.05   361.8  632.96   391.2  645.32   410.7  653.93
#Mann= 3 , 0 , 0
       0     .08       0   234.7    .045       0   254.6      .1       0
Bank Sta=234.7,254.6
XS Rating Curve= 0 ,0
Exp/Cntr=0.3,0.1

Type RM Length L Ch R = 1 ,7127.7  ,491.8,492.8,493.8
XS GIS Cut Line= 2
      1869705.77      560921.709     1869427.992      560560.598
#Sta/Elev= 30
       0  659.37    19.4  647.72    29.1  643.21    38.8  639.67    58.2  633.03
    67.8  631.13    77.6  630.43    87.2  629.88   193.9  624.29     223  622.94
   261.7   619.4   271.4  618.17   290.8  613.09   300.5  612.28   310.2  612.42
   319.9  614.21   329.6  617.25   339.3   618.6     349  619.61   358.7  622.67
   368.4  628.26     378  632.28   387.7  633.83   397.4   634.3   407.1  635.44
   416.8  639.34   426.5  646.16   436.2  654.07   445.9  661.82   455.6  668.53
#Mann= 3 , 0 , 0
       0     .08       0   290.8    .045       0   310.2      .1       0
Bank Sta=290.8,310.2
XS Rating Curve= 0 ,0
Exp/Cntr=0.3,0.1

Type RM Length L Ch R = 1 ,6634.9  ,512.3,504.4,497
XS GIS Cut Line= 4
     1870066.881      560598.792     1870016.534      560531.084
     1869874.173      560327.959     1869789.103       560242.89
#Sta/Elev= 30
       0  651.17     9.4  648.51    46.9  639.03      75   630.8    84.4  628.17
    93.9  626.54   103.5  625.89   132.1   624.3   141.6  623.62   189.3  619.48
   198.9  617.92   217.9   612.8   227.5  612.23     237   612.2   246.6  612.68
   256.1  614.66   265.6  617.93   275.2  620.37   284.7  622.13   322.9  628.43
   341.7  633.26   350.9  634.39   360.2  634.82   369.4  636.89   378.7  640.78
     388  646.38   415.7  664.01     425  669.58   434.2  674.63   452.7  684.09
#Mann= 3 , 0 , 0
       0     .08       0   217.9    .045       0   246.6      .1       0
Bank Sta=217.9,246.6
XS Rating Curve= 0 ,0
Exp/Cntr=0.3,0.1

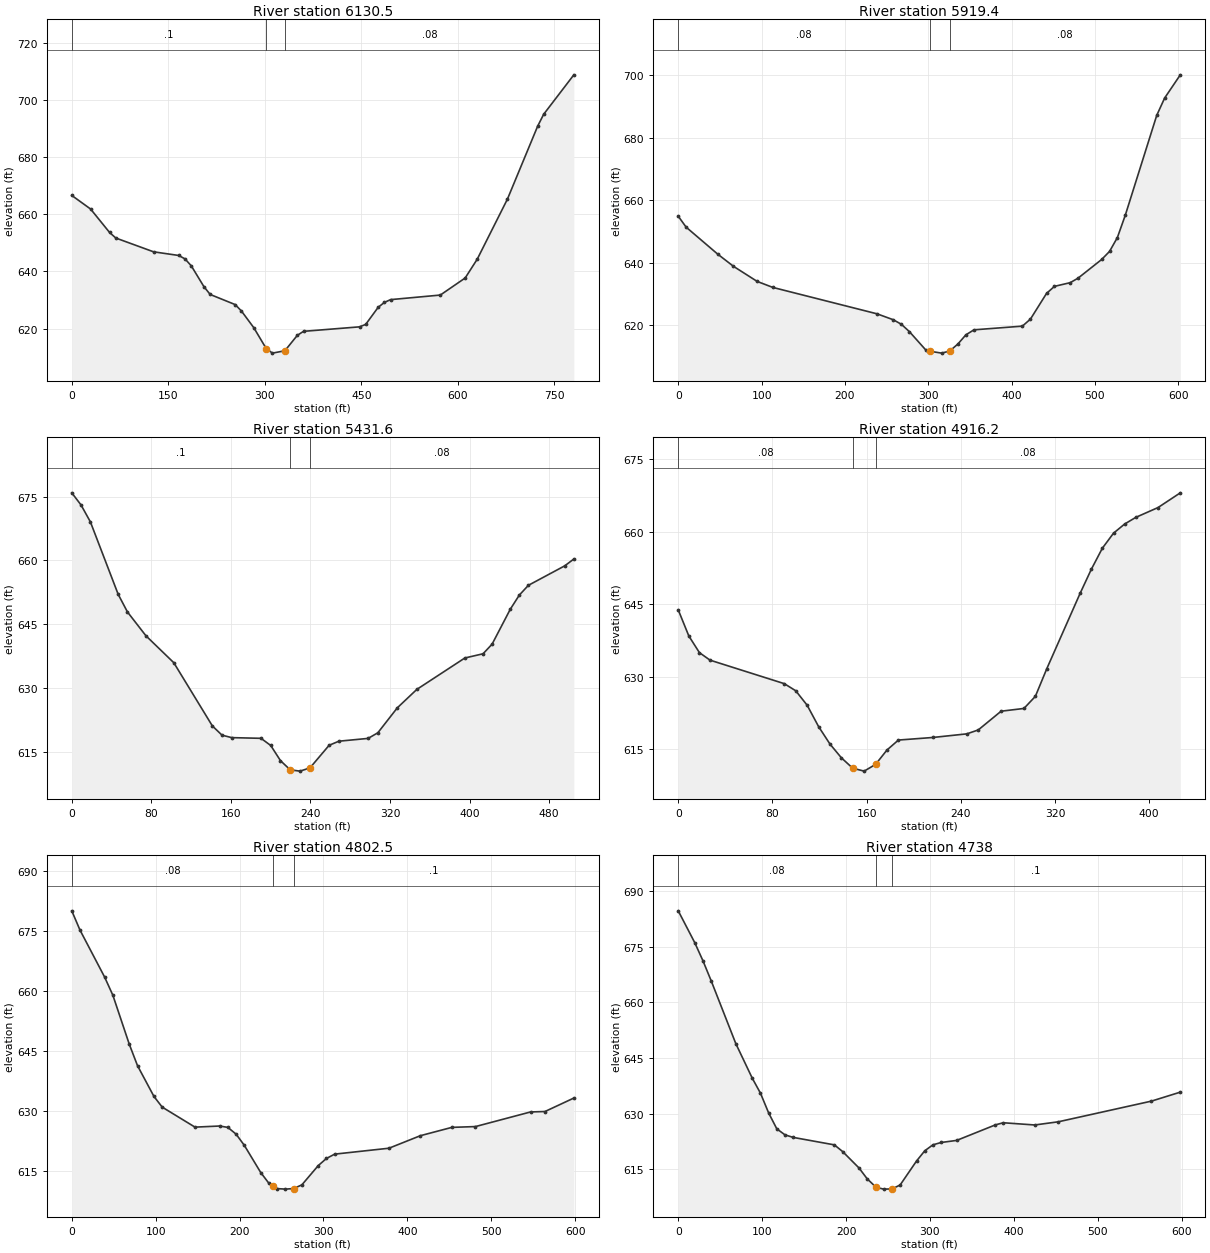
Type RM Length L Ch R = 1 ,6130.5  ,211.8,211.1,210.8
XS GIS Cut Line= 4
     1870445.353      560400.876     1870395.006      560171.709
      1870089.45      559951.223     1870046.048      559788.028
#Sta/Elev= 30
       0  666.61    29.3  661.84    58.7  653.66    68.4   651.7   127.1  646.87
   166.2  645.59     176  644.39   185.8  641.94   205.3   634.7   215.1  631.94
     254  628.39   263.6  626.17   282.9   620.3   302.3  612.96   311.9   611.4
   331.2  612.23   350.6  617.64   360.2  619.03   447.2   620.6   456.8  621.46
   476.2  627.44   485.8  629.15   495.5  630.13   572.8  631.73   611.4   637.7
   630.2  644.31   677.1  665.33     724  690.82   733.4  695.02   780.3  708.83
#Mann= 3 , 0 , 0
       0      .1       0   302.3    .045       0   331.2     .08       0
Bank Sta=302.3,331.2
XS Rating Curve= 0 ,0
Exp/Cntr=0.3,0.1

Type RM Length L Ch R = 1 ,5919.4  ,490.7,487.8,482.9
XS GIS Cut Line= 4
     1870629.381      560044.973     1870485.284      559998.098
     1870240.492      559841.848     1870139.798      559716.848
#Sta/Elev= 30
       0  654.94     9.5  651.43    47.4  642.79    66.3  638.89    94.7  634.06
   113.6  632.13   238.6  623.68     258  621.79   267.7  620.34   277.4  617.97
   296.7   612.2   301.5  611.72   316.1   611.1   325.8  611.79   335.5  614.01
   345.1  616.95   354.8  618.56   412.9  619.74   422.6     622   441.9  630.22
   451.4  632.48   470.3  633.66   479.7   635.1     508  641.08   517.5  643.67
   526.9  648.11   536.4  655.27   574.1  687.22   583.6  692.78   602.4  700.21
#Mann= 3 , 0 , 0
       0     .08       0   301.5    .045       0   325.8     .08       0
Bank Sta=301.5,325.8
XS Rating Curve= 0 ,0
Exp/Cntr=0.3,0.1

Type RM Length L Ch R = 1 ,5431.6  ,514.8,515.5,515.1
XS GIS Cut Line= 4
       1870808.2       559617.89     1870710.978      559562.334
     1870462.714      559446.015     1870348.131      559414.765
#Sta/Elev= 30
       0   675.9     9.3  673.05    18.7  669.08    46.7     652      56  647.87
    74.6  642.26   102.6  635.93   141.4  621.05   151.1  618.88   160.9   618.3
   190.3  618.14   200.1  616.45   209.9  612.88   219.7  610.72   229.5  610.42
   239.5  611.17   258.8   616.5   268.6  617.46     298  618.12   307.8  619.44
   327.4  625.32     347  629.65   395.3  637.04   413.6  638.03   422.7   640.3
     441  648.52   450.1  651.85   459.2  654.14   495.8  658.73   504.9  660.33
#Mann= 3 , 0 , 0
       0      .1       0   219.7    .045       0   239.5     .08       0
Bank Sta=219.7,239.5
XS Rating Curve= 0 ,0
Exp/Cntr=0.3,0.1

Type RM Length L Ch R = 1 ,4916.2  ,114.6,113.7,112.8
XS GIS Cut Line= 4
      1870924.52      559104.001     1870842.923      559065.806
     1870641.534       558970.32     1870530.423       558992.89
#Sta/Elev= 30
       0  643.84       9  638.44      18     635      27  633.45    90.1  628.59
    99.8  627.12   109.5  624.13   119.2  619.72   128.9   616.1   138.6  613.26
   148.2  611.12   157.9  610.52   167.6  611.91   177.3  614.89     187  616.94
   216.1  617.47   245.1  618.22   254.8  619.03   274.2   622.9   293.6  623.47
   303.3  625.97     313  631.68   341.3  647.25   350.8  652.21   360.2  656.58
   369.7  659.69   379.1  661.57   388.6  662.95   407.5  664.98   426.4  668.02
#Mann= 3 , 0 , 0
       0     .08       0   148.2    .045       0   167.6     .08       0
Bank Sta=148.2,167.6
XS Rating Curve= 0 ,0
Exp/Cntr=0.3,0.1

Type RM Length L Ch R = 1 ,4802.5  ,64.5,64.5,64.5
XS GIS Cut Line= 5
     1871039.103       559024.14     1870750.909      558900.876
     1870686.673       558907.82      1870518.27      558919.973
     1870469.659      558937.334
#Sta/Elev= 30
       0  680.05     9.8  675.23    39.2  663.45      49  658.91    68.6  646.63
    78.4  641.27      98  633.57   107.8  630.91   146.9   625.9   176.3  626.18
   186.1  625.83   195.9  624.14   205.7  621.34   225.3  614.52   235.1  611.81
   239.8  611.19   244.9  610.51   254.7  610.38   264.5  610.53   274.3  611.45
   293.9  616.29   303.6  618.06   313.4  619.14   378.1  620.62   415.6  623.76
   453.1  625.84   481.2  626.04   546.9   629.7   564.1  629.81   598.5  633.18
#Mann= 3 , 0 , 0
       0     .08       0   239.8    .045       0   264.5      .1       0
Bank Sta=239.8,264.5
XS Rating Curve= 0 ,0
Exp/Cntr=0.3,0.1

Type RM Length L Ch R = 1 ,4738    ,172.2,174.7,177.2
XS GIS Cut Line= 5
     1871056.464       558961.64      1870768.27      558838.376
     1870704.034       558845.32     1870535.631      558857.473
      1870487.02      558874.834
#Sta/Elev= 30
       0   684.7    19.6  676.16    29.4  671.27    39.2  665.88    68.6  648.93
    88.2  639.61      98  635.56   107.8  630.21   117.5  625.94   127.3  624.31
   137.1  623.63   186.1  621.62   195.9  619.83   215.5  615.39   225.3  612.45
   235.9  610.18   244.9  609.69   254.7  609.74   264.5   610.8   284.1  617.28
   293.9  620.03   303.6  621.63   313.4  622.26   331.9  622.82   378.1  627.01
   387.4  627.58     425  626.98   453.1  627.84   564.1  633.41   598.5  635.83
#Mann= 3 , 0 , 0
       0     .08       0   235.9    .045       0   254.7      .1       0
Bank Sta=235.9,254.7
XS Rating Curve= 0 ,0
Exp/Cntr=0.3,0.1

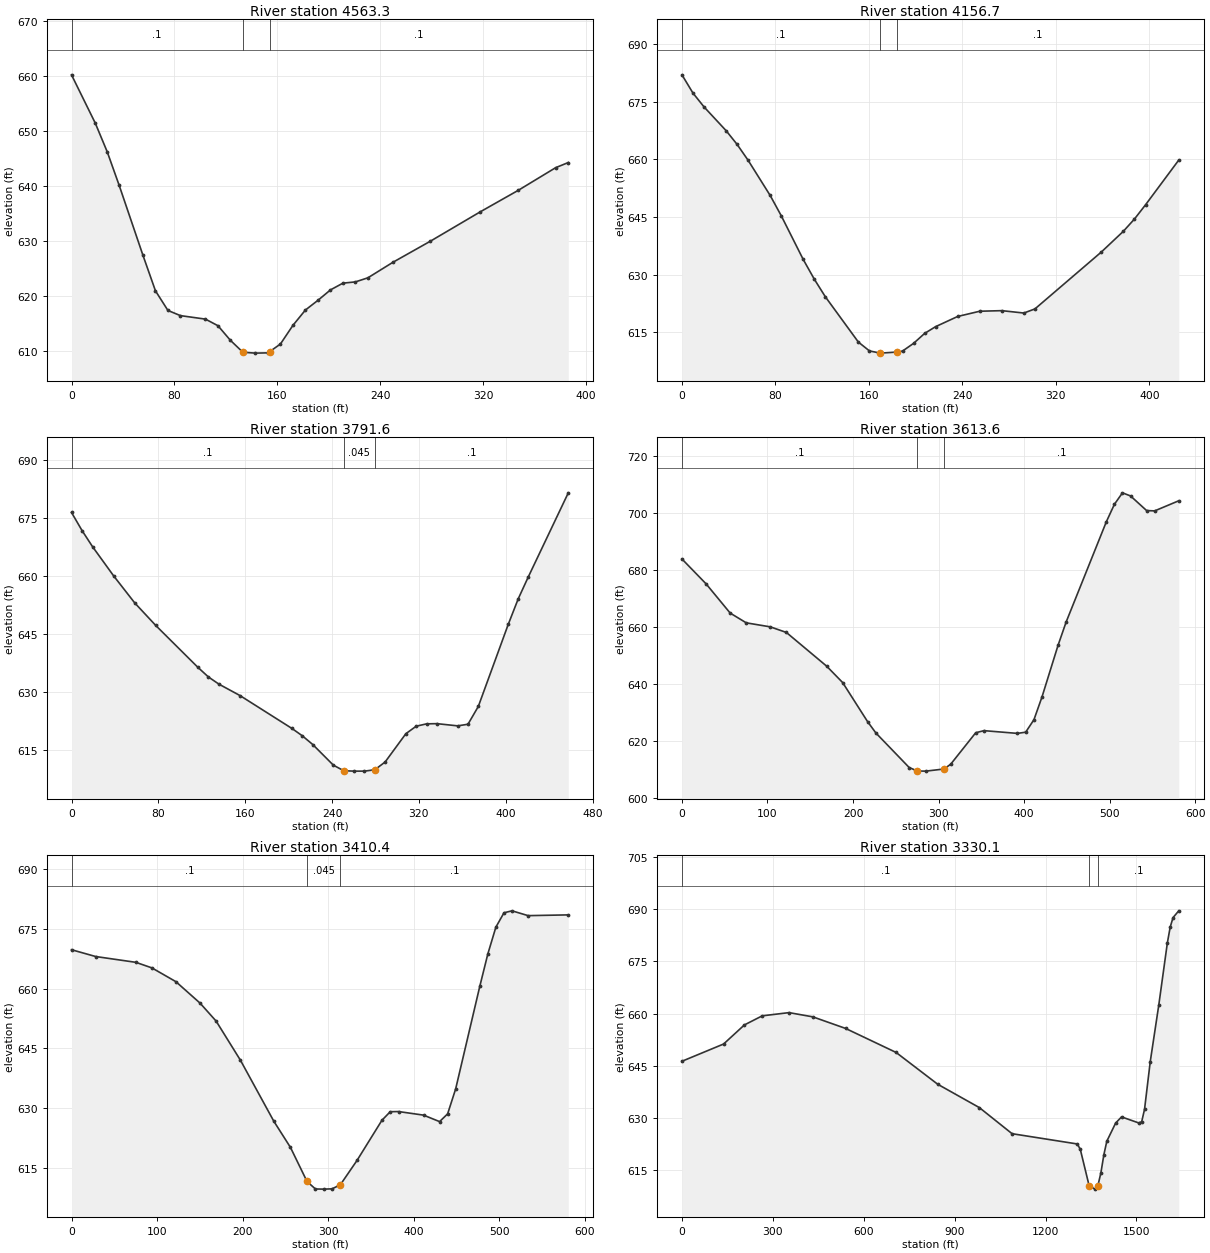
Type RM Length L Ch R = 1 ,4563.3  ,409,406.6,404
XS GIS Cut Line= 4
     1871046.048      558770.667     1870992.228      558756.778
     1870806.464      558650.876     1870717.923      558574.487
#Sta/Elev= 29
       0  660.28    18.5  651.48    27.8  646.25    37.1  640.14    55.6   627.4
    65.3  620.95      75  617.38    84.7  616.44   104.2   615.8   113.9   614.6
   123.6  611.94   133.3  609.77   143.1  609.61   152.8  609.66   154.2  609.89
   162.5  611.27   172.2  614.66   181.9  617.45   191.7  619.23   201.4  621.12
   211.1  622.35   220.8  622.58   230.5  623.32     250  626.15   279.2     630
   318.1  635.36   347.4  639.24   376.6  643.38   386.4  644.31
#Mann= 3 , 0 , 0
       0      .1       0   133.3    .045       0   154.2      .1       0
Bank Sta=133.3,154.2
XS Rating Curve= 0 ,0
Exp/Cntr=0.3,0.1

Type RM Length L Ch R = 1 ,4156.7  ,363,365.2,367.3
XS GIS Cut Line= 4
     1871198.825      558385.251      1871089.45      558355.737
     1870898.478       558274.14       1870808.2      558222.056
#Sta/Elev= 30
       0     682     9.4  677.26    18.9  673.65    37.8  667.47    47.2   663.9
    56.6  659.78    75.5  650.62      85  645.33   103.8  633.96   113.3  628.82
   122.7  624.27     151  612.47   160.5  610.17   169.2  609.64   169.9   609.6
   184.2  609.88   188.8  610.14   198.2  612.13   207.7  614.73   217.1  616.49
     236  619.14   254.9   620.5   273.8  620.65   292.6  620.03   302.1   621.1
   358.9  635.89   377.8   641.3   387.3  644.49   396.8   648.2   425.2  659.82
#Mann= 3 , 0 , 0
       0      .1       0   169.2    .045       0   184.2      .1       0
Bank Sta=169.2,184.2
XS Rating Curve= 0 ,0
Exp/Cntr=0.3,0.1

Type RM Length L Ch R = 1 ,3791.6  ,179.5,178,176.4
XS GIS Cut Line= 4
     1871349.867      558112.681     1871207.506      558029.348
     1871023.478      557928.653     1870954.034      557883.515
#Sta/Elev= 30
       0  676.46     9.7  671.78    19.4   667.6    38.8  660.07    58.2  653.09
    77.6  647.25   116.4  636.43   126.1  633.94   135.8  632.08   155.2  629.13
   203.1  620.62   212.6  618.73   222.2  616.48   241.2  611.14   250.8   609.7
   260.3   609.6   269.8   609.6   279.4  609.95   288.9  611.97     308  619.28
   317.5  621.21   327.1  621.82   336.6  621.87   355.7   621.3   365.2  621.72
   374.7  626.31   402.3  647.54   411.5  654.15   420.8  659.83   457.6  681.53
#Mann= 3 , 0 , 0
       0      .1       0   250.8    .045       0   279.4      .1       0
Bank Sta=250.8,279.4
XS Rating Curve= 0 ,0
Exp/Cntr=0.3,0.1

Type RM Length L Ch R = 1 ,3613.6  ,203.1,203.2,203.1
XS GIS Cut Line= 4
     1871476.603      557956.431       1871308.2      557873.098
     1871105.075      557779.348     1870952.298      557706.431
#Sta/Elev= 30
       0  684.02    28.2   675.3    56.4  665.04    75.2  661.62   103.3  660.21
   122.1  658.25   169.1  646.45   187.9  640.67   217.1  626.94   226.8  622.97
   265.7  610.86   275.4  609.64   285.2   609.6   306.5  610.35   314.3  612.05
   343.5  623.07   353.2   623.8   392.2  622.84   401.9  623.26   411.6  627.65
     421  635.63   439.8  653.77   449.2   661.9   496.2  697.06   505.7  703.23
   515.1  707.23   524.5  706.14   543.3  701.01   552.7  700.89   580.9  704.44
#Mann= 3 , 0 , 0
       0      .1       0   275.4    .045       0   306.5      .1       0
Bank Sta=275.4,306.5
XS Rating Curve= 0 ,0
Exp/Cntr=0.3,0.1

Type RM Length L Ch R = 1 ,3410.4  ,80.4,80.3,80.4
XS GIS Cut Line= 4
     1871591.186      557788.028     1871422.784      557704.695
     1871219.659      557610.945     1871066.881      557538.028
#Sta/Elev= 30
       0  669.81    28.2   668.1    75.2  666.64      94  665.24   122.1  661.77
   150.3  656.38   169.1  651.86   197.6  641.99   236.5   626.7     256   620.1
   275.4  611.52   285.2  609.64   294.8   609.6   304.6  609.67   314.3  610.68
   333.8   616.8     363  626.92   372.7  629.07   382.4  629.11   411.6  628.21
   430.4  626.58   439.8  628.53   449.2  634.81   477.4   660.6   486.8  668.74
   496.2  675.48   505.7   679.1   515.1  679.59   533.9  678.38   580.9  678.57
#Mann= 3 , 0 , 0
       0      .1       0   275.4    .045       0   314.3      .1       0
Bank Sta=275.4,314.3
XS Rating Curve= 0 ,0
Exp/Cntr=0.3,0.1

Type RM Length L Ch R = 1 ,3330.1  ,87.5,87.5,87.5
XS GIS Cut Line= 4
     1872594.405      558176.438     1871469.659      557638.723
     1871266.534      557544.973     1871113.756      557472.056
#Sta/Elev= 30
       0   646.3   137.4  651.25   206.1  656.73     265  659.34   353.4  660.26
   431.9  659.05   539.9  655.73   706.8  648.83   844.2   639.7   981.6     633
  1089.6  625.51    1305  622.56  1314.8     621  1343.9  610.58  1363.4   609.6
  1372.7  610.54  1382.8  614.31  1392.6   619.5  1402.3  623.36  1431.5  628.58
  1450.9  630.33    1508  628.59  1517.4  628.95  1526.8  632.53  1545.6  646.18
  1573.8  662.44  1602.1  680.28  1611.5  684.82  1620.9  687.54  1639.7  689.48
#Mann= 3 , 0 , 0
       0      .1       0  1343.9    .045       0  1372.7      .1       0
Bank Sta=1343.9,1372.7
XS Rating Curve= 0 ,0
Exp/Cntr=0.3,0.1

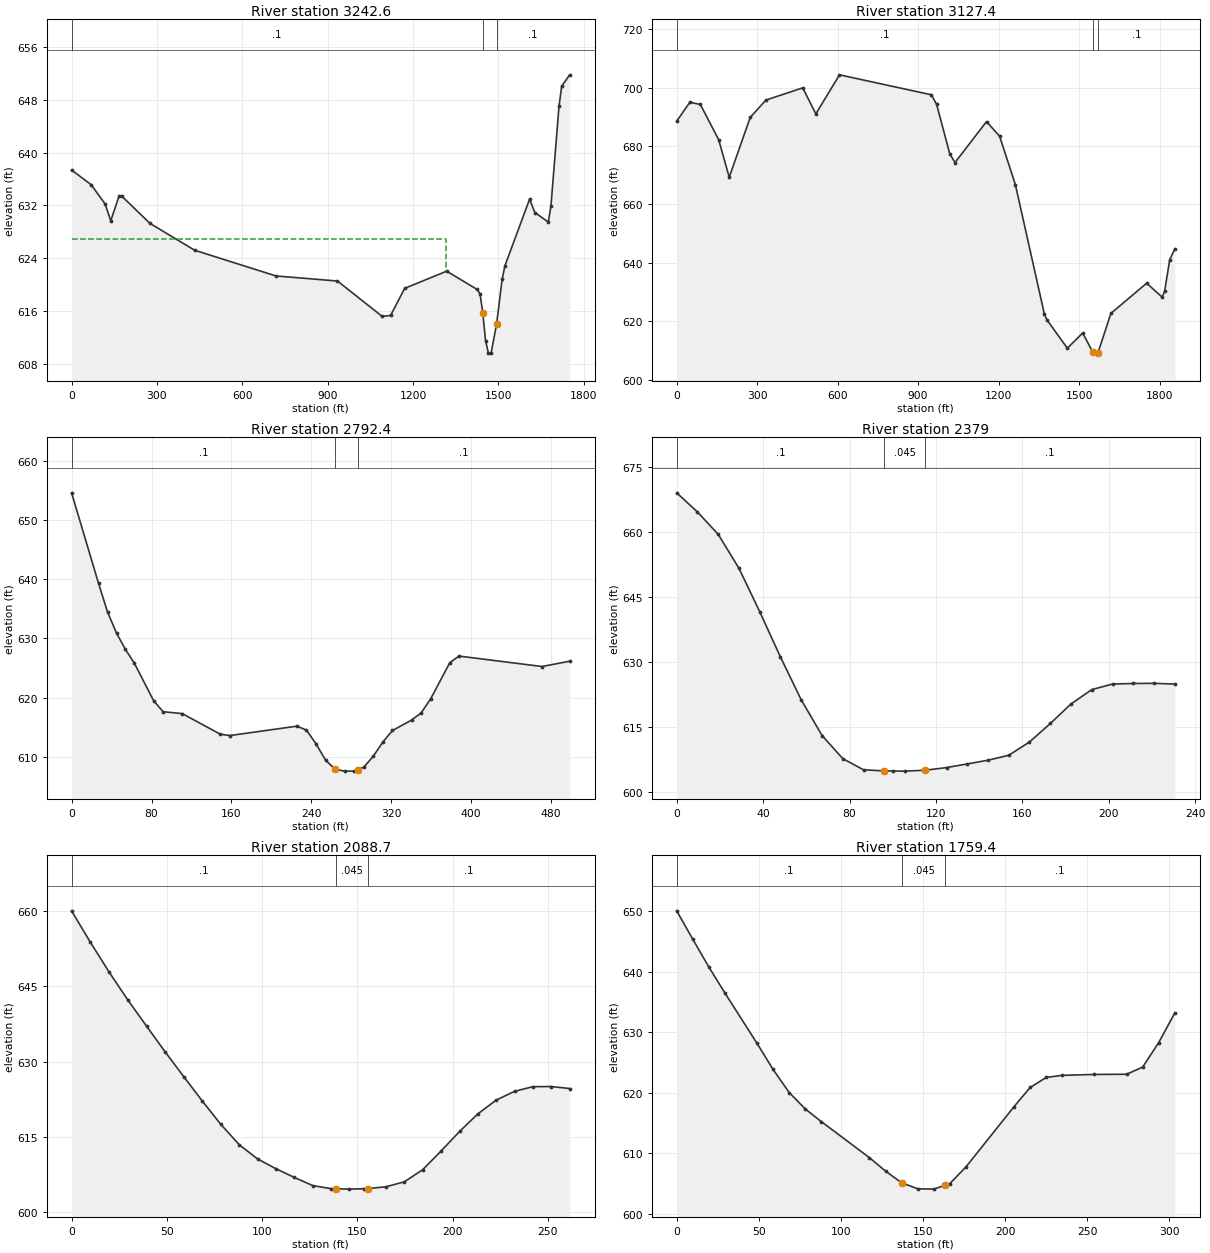
Type RM Length L Ch R = 1 ,3242.6  ,124.7,115.2,105
XS GIS Cut Line= 4
     1872740.239      558147.792     1871514.798       557564.07
     1871311.673       557470.32     1871158.895      557397.403
#Sta/Elev= 30
       0  637.36    68.8  635.14     118  632.21   137.7  629.67   167.2  633.47
     177  633.38   275.4  629.28   432.8  625.21     718  621.32   934.4  620.55
  1091.8  615.18  1121.3  615.35  1170.5  619.44    1318  622.04  1425.4  619.27
  1435.2  618.62  1444.9  615.76  1454.6  611.53  1464.4  609.69  1474.1  609.63
  1493.5  614.04    1513  620.83  1522.7  622.85  1609.3  632.94  1628.1  630.92
  1675.1  629.48  1684.5  631.92  1712.8  647.03  1722.2  650.06  1750.4  651.78
#Mann= 3 , 0 , 0
       0      .1       0  1444.9    .045       0  1493.5      .1       0
#XS Ineff= 2 , 0
         1316.52  626.94
Permanent Ineff=
       F       F
Bank Sta=1444.9,1493.5
XS Rating Curve= 0 ,0
Exp/Cntr=0.3,0.1

Type RM Length L Ch R = 1 ,3127.4  ,348.5,335,321.5
XS GIS Cut Line= 4
     1872917.322      557960.292     1871659.763      557415.575
     1871421.048      557415.575     1871175.822      557378.682
#Sta/Elev= 30
       0  688.49      49  694.95    88.1  694.21   156.6  682.12   195.8   669.3
   274.1  689.78   332.8  695.72   469.9  699.89   518.8  690.98   606.9  704.35
   949.5  697.52   969.1  694.22  1018.1  677.32  1037.6  674.33  1155.1  688.35
    1204  683.31  1262.8  666.72  1370.5   622.6    1380  620.54  1456.4   610.8
  1513.7  615.99  1551.9  609.33  1561.4  609.11    1571   609.3  1618.7   622.7
  1752.2  633.04  1809.5  628.29    1819  630.24  1838.1  641.07  1857.2   644.8
#Mann= 3 , 0 , 0
       0      .1       0  1551.9    .045       0    1571      .1       0
Bank Sta=1551.9,1571
XS Rating Curve= 0 ,0
Exp/Cntr=0.3,0.1

Type RM Length L Ch R = 1 ,2792.4  ,425.4,413.5,402
XS GIS Cut Line= 4
     1871531.291      557002.814     1871473.999      557028.856
     1871210.978      557203.335     1871101.603      557252.814
#Sta/Elev= 30
       0  654.58      27  639.29      36  634.45      45  630.89    53.9  628.15
    62.9   625.8    82.1   619.5    91.6  617.63   110.8  617.31     149  613.82
   158.6  613.61   225.5  615.19   235.1  614.53   244.7  612.19   254.2  609.47
   263.8   607.9   273.4   607.6   282.9   607.6   286.8  607.87   292.5  608.27
     302  610.11   311.6  612.52   321.2  614.46   340.3  616.21   349.9  617.43
   359.4   619.8   378.6  625.91   387.8  627.02   470.9  625.26   498.6  626.16
#Mann= 3 , 0 , 0
       0      .1       0   263.8    .045       0   286.8      .1       0
Bank Sta=263.8,286.8
XS Rating Curve= 0 ,0
Exp/Cntr=0.3,0.1

Type RM Length L Ch R = 1 ,2379    ,288.2,290.3,292.3
XS GIS Cut Line= 2
     1871013.061      556830.939     1870908.895      557036.669
#Sta/Elev= 27
       0  668.98     9.6  664.57    19.2   659.4    28.8  651.57    38.4  641.57
      48   631.1    57.6  621.22    67.3  612.92    76.9  607.59    86.5  605.01
    96.1  604.76     100  604.74   105.7  604.71     115  604.92   115.3  604.93
   124.9  605.53   134.5  606.37   144.1  607.23   153.7  608.37   163.3  611.43
     173  615.73   182.6  620.25   192.2  623.55   201.8  624.82   211.4  624.95
     221  624.98   230.6  624.82
#Mann= 3 , 0 , 0
       0      .1       0    96.1    .045       0     115      .1       0
Bank Sta=96.1,115
XS Rating Curve= 0 ,0
Exp/Cntr=0.3,0.1

Type RM Length L Ch R = 1 ,2088.7  ,319.8,329.3,338.3
XS GIS Cut Line= 3
     1870773.478       556718.96     1870734.416      556763.231
     1870627.645      556935.106
#Sta/Elev= 30
       0  660.04     9.8  653.82    19.7  647.84    29.5  642.29    39.4  637.04
    49.2  631.89      59  626.94    68.7  622.11    78.3  617.51      88  613.44
    97.6  610.62   107.2  608.67   116.8  606.95   126.5  605.31   136.1   604.7
   138.6  604.67   145.8   604.6   153.6  604.68   155.4   604.7     165  605.07
   174.7  606.07   184.3  608.49   193.9  612.19   203.6  616.09   213.2  619.59
   222.8  622.33   232.5  624.09   242.1  625.01   251.7  625.04   261.4  624.64
#Mann= 3 , 0 , 0
       0      .1       0   138.6    .045       0   155.4      .1       0
Bank Sta=138.6,155.4
XS Rating Curve= 0 ,0
Exp/Cntr=0.3,0.1

Type RM Length L Ch R = 1 ,1759.4  ,305.3,306.4,307.1
XS GIS Cut Line= 2
     1870570.353      556541.877     1870320.353      556713.752
#Sta/Elev= 26
       0  650.07     9.8  645.37    19.6  640.77    29.4  636.47    48.9  628.17
    58.7  623.85    68.5  620.03    78.3  617.32    88.1  615.22   117.4  609.26
   127.2  607.04     137   605.1   146.8  604.12   156.6  604.06   163.7  604.73
   166.4  604.99   176.2  607.74   205.5  617.71   215.3  620.87   225.1  622.53
   234.9  622.87   254.4  623.02     274  623.05   283.8  624.23   293.6   628.3
   303.4   633.2
#Mann= 3 , 0 , 0
       0      .1       0     137    .045       0   163.7      .1       0
Bank Sta=137,163.7
XS Rating Curve= 0 ,0
Exp/Cntr=0.3,0.1

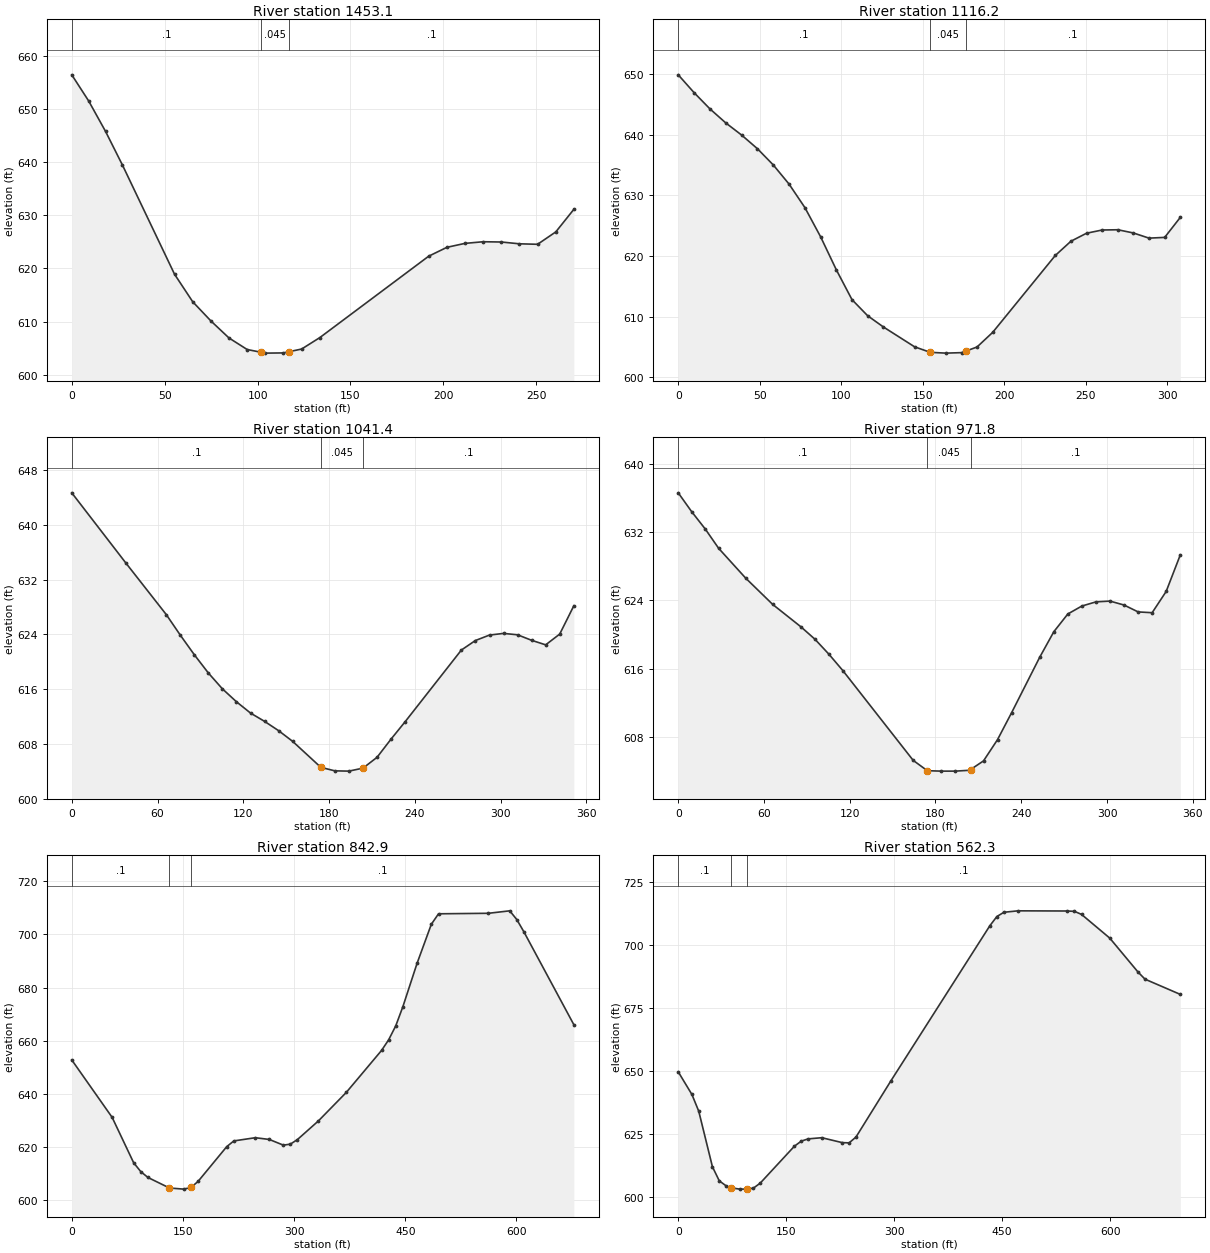
Type RM Length L Ch R = 1 ,1453.1  ,337.9,336.8,335.7
XS GIS Cut Line= 3
     1870364.624      556294.481     1870341.186      556333.544
     1870151.082      556453.335
#Sta/Elev= 24
       0  656.51     9.1  651.58    18.2  645.83    27.3  639.48    55.3  618.92
    65.1  613.72    74.9   610.1    84.6   606.9    94.4  604.72   101.8  604.21
   104.2  604.04   113.9  604.08   116.8   604.3   123.7  604.81   133.5  606.97
   192.1  622.32   201.9  623.99   211.6  624.73   221.4  625.04   231.2  624.99
   240.9  624.65   250.7  624.56   260.5   626.9   270.2  631.15
#Mann= 3 , 0 , 0
       0      .1       0   101.8    .045       0   116.8      .1       0
Bank Sta=101.8,116.8
XS Rating Curve= 0 ,0
Exp/Cntr=0.3,0.1

Type RM Length L Ch R = 1 ,1116.2  ,75.2,74.8,74.6
XS GIS Cut Line= 3
     1870239.081      556066.924     1870152.276      556056.507
      1869971.72      556183.243
#Sta/Elev= 30
       0  649.86     9.7  646.93    19.4  644.26    29.1  641.95    38.9  639.93
    48.6  637.68    58.3  635.01      68  631.85    77.7  627.98    87.4  623.14
      97  617.72   106.6  612.81   116.2  610.16   125.8  608.32     145  605.04
   154.6  604.13   164.2     604   173.8  604.08   176.5  604.34   183.3  605.01
   192.9  607.42   231.3  620.09   240.9  622.44   250.5  623.76   260.1  624.29
   269.7  624.33   279.2   623.8   288.8  622.95   298.4  623.07     308  626.37
#Mann= 3 , 0 , 0
       0      .1       0   154.6    .045       0   176.5      .1       0
Bank Sta=154.6,176.5
XS Rating Curve= 0 ,0
Exp/Cntr=0.3,0.1

Type RM Length L Ch R = 1 ,1041.4  ,69.7,69.7,69.7
XS GIS Cut Line= 3
     1870214.776      555927.077     1870157.267      555959.629
     1869926.147      556126.729
#Sta/Elev= 28
       0  644.68    37.8  634.44    66.1   626.9    75.9   623.9    85.8  621.01
    95.6  618.35   105.4  616.04   115.2  614.16   125.1   612.5   134.9  611.29
   144.8  609.92   154.6  608.36   174.3  604.57   184.1  604.06   193.9  604.02
   203.8  604.46   213.6  606.04   223.4   608.7   233.3  611.25   272.6  621.71
   282.4   623.1   292.3   623.9   302.1  624.14   311.9  623.94   321.8  623.13
   331.6  622.47   341.4  624.04   351.3  628.18
#Mann= 3 , 0 , 0
       0      .1       0   174.3    .045       0   203.8      .1       0
Bank Sta=174.3,203.8
XS Rating Curve= 0 ,0
Exp/Cntr=0.3,0.1

Type RM Length L Ch R = 1 ,971.8   ,127.2,128.9,130.7
XS GIS Cut Line= 3
     1870172.458      555871.738     1870114.949       555904.29
      1869883.83      556071.391
#Sta/Elev= 30
       0  636.62     9.4  634.41    18.9  632.38    28.3  630.11    47.2  626.62
    66.1  623.54    85.8  620.92    95.6  619.47   105.4  617.71   115.2  615.78
   164.4  605.26   174.3  604.05   184.1     604   193.9     604   203.8   604.1
   204.5  604.18   213.6   605.2   223.4  607.69   233.3  610.86   252.9  617.34
   262.8  620.34   272.6  622.42   282.4  623.35   292.3  623.84   302.1  623.93
   311.9  623.47   321.8  622.66   331.6  622.57   341.4  625.06   351.3  629.35
#Mann= 3 , 0 , 0
       0      .1       0   174.3    .045       0   204.5      .1       0
Bank Sta=174.3,204.5
XS Rating Curve= 0 ,0
Exp/Cntr=0.3,0.1

Type RM Length L Ch R = 1 ,842.9   ,280.6,280.6,280.6
XS GIS Cut Line= 5
     1870041.165      555780.466     1870013.387      555827.341
     1869848.456      555928.035     1869798.109      556070.396
     1869607.137      556273.521
#Sta/Elev= 30
       0  652.71    54.5  631.06    83.5  613.96    93.1  610.63   102.8  608.41
   131.8  604.45   151.1  604.02   160.8  604.64   170.4  606.92   209.1  620.03
   218.7  622.19   247.7   623.4   266.6  622.74   285.5   620.6   294.9  620.97
   304.4  622.68   332.7   629.7   370.4  640.46     418  656.29   427.6   660.3
   437.2  665.58   446.8  672.79     466  689.18   485.2  703.86   494.9   707.8
   562.2  707.99     591  708.92   600.6   705.6   610.2  700.95   677.5     666
#Mann= 3 , 0 , 0
       0      .1       0   131.8    .045       0   160.8      .1       0
Bank Sta=131.8,160.8
XS Rating Curve= 0 ,0
Exp/Cntr=0.3,0.1

Type RM Length L Ch R = 1 ,562.3   ,364,366.1,368.2
XS GIS Cut Line= 3
     1869862.345      555591.229     1869643.595       555724.91
     1869423.109      556106.854
#Sta/Elev= 30
       0  649.77      19   640.8    28.5  634.16    47.5  612.15      57  606.58
    66.5  604.59    73.8   603.8    85.4  603.29      95  603.31   104.4  603.68
   113.9  605.67   161.4  620.31   170.9  622.31   180.4   623.2   199.4  623.67
   227.9  621.71   237.4  621.63   246.9  623.93   295.6  646.29   432.8  707.65
   442.6  711.32   452.4  713.01     472  713.58   540.6  713.51   550.4  713.37
   560.2  712.16   599.4  702.77   638.6  689.34   648.4  686.49   697.4  680.46
#Mann= 3 , 0 , 0
       0      .1       0    73.8    .045       0      95      .1       0
Bank Sta=73.8,95
XS Rating Curve= 0 ,0
Exp/Cntr=0.3,0.1

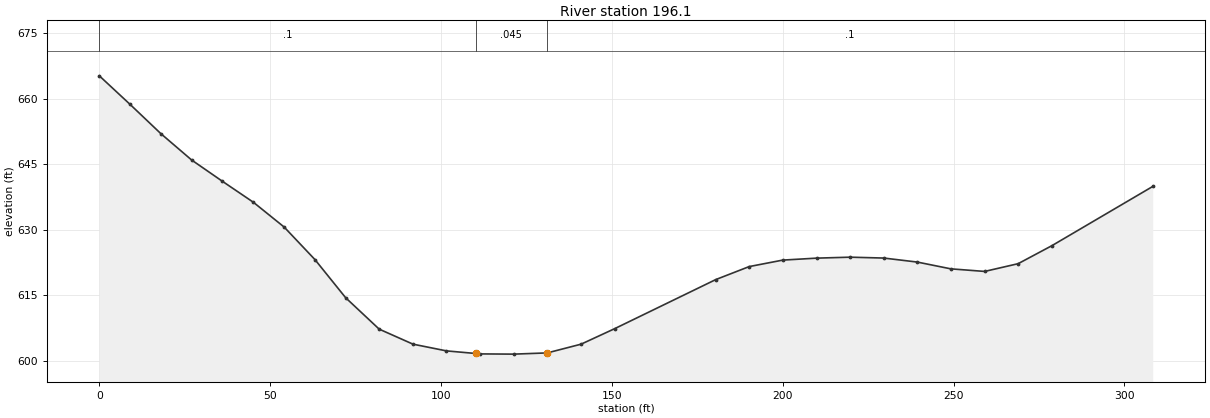
Type RM Length L Ch R = 1 ,196.1   ,199.4,196.1,192.9
XS GIS Cut Line= 3
     1869674.845      555273.521     1869618.044      555317.923
     1869406.016      555421.984
#Sta/Elev= 30
       0  665.21       9  658.67      18  651.98      27  645.95      36  641.08
    45.1  636.26    54.1  630.59    63.1  623.15    72.1  614.41    81.9  607.23
    91.8  603.79   101.6  602.25   110.1  601.66   111.5  601.56   121.3  601.51
   131.1  601.79     141  603.79   150.8  607.33   180.4  618.57   190.2  621.55
     200  623.03   209.9  623.48   219.7   623.7   229.6   623.5   239.4  622.58
   249.2  621.03   259.1  620.44   268.9  622.21   278.8  626.34   308.3  639.89
#Mann= 3 , 0 , 0
       0      .1       0   110.1    .045       0   131.1      .1       0
Bank Sta=110.1,131.1
XS Rating Curve= 0 ,0
Exp/Cntr=0.3,0.1

Chan Stop Cuts=-1
Use User Specified Reach Order=0
Composite Channel Slope=5